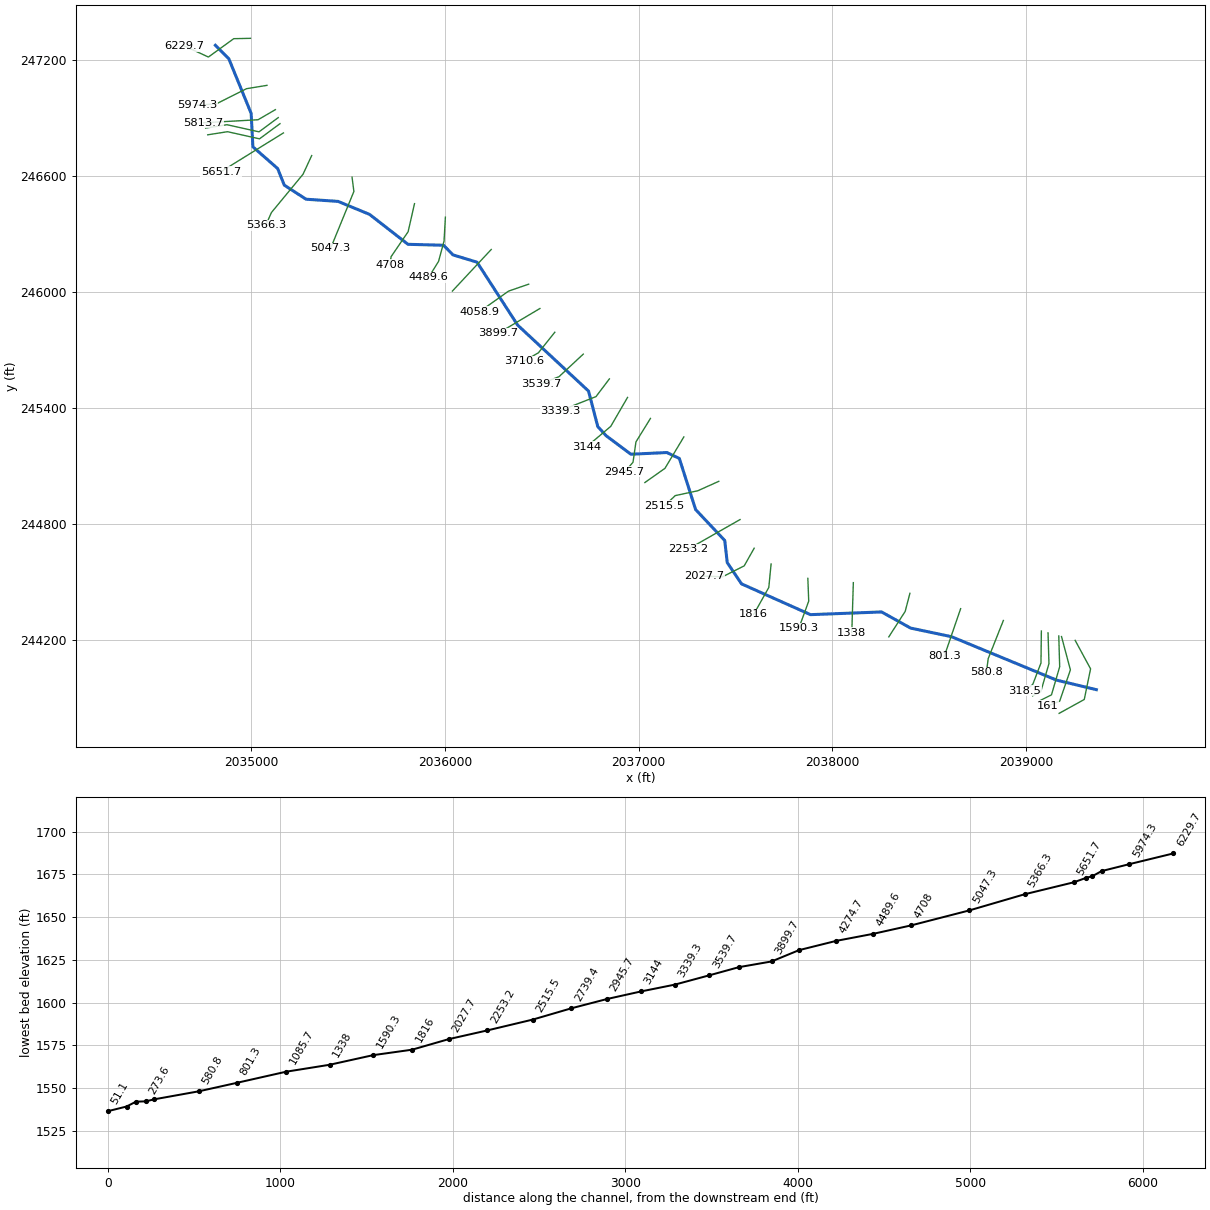
--- BOONECK.prj (project) ---

Proj Title=BOONECK
Current Plan=p01
Default Exp/Contr=0,0
English Units
Geom File=g01
Flow File=f01
Plan File=p01
BEGIN DESCRIPTION:
END DESCRIPTION:
DSS Export Rating Curves= 0
DSS Export Rating Curve Sorted= 0
DSS Export Volume Flow Curves= 0
DXF OffsetX= 0
DXF OffsetY= 0
DXF ScaleX= 0
DXF ScaleY= 0

--- BOONECK.p01 (plan) ---

Plan Title=Floodplain
Program Version=4.00
Geom File=g01
Flow File=f01
K Sum by GR=0
Std Step Tol=0.01
Critical Tol=0.01
Num of Std Step Trials=20
Max Error Tol=0.3
Flow Tol Ratio=0.001
Split Flow NTrial=30
Split Flow Tol=0.02
Split Flow Ratio=0.02
Log Output Level=0
Friction Slope Method=1
Unsteady Friction Slope Method=2
Unsteady Bridges Friction Slope Method=1
Global Log Level=0
CheckData=False
Run HTab=0
Run UNet=0
Run PostProcess=0
UNET Theta=0
UNET Theta Warmup=0
UNET ZTol=0
UNET ZSATol=0
UNET MxIter=0
UNET MaxInSteps=0
UNET DtIC=0
UNET DtMin=0
UNET MaxCRTS=0
UNET WFStab=0
UNET SFStab=0
UNET WFX=0
UNET SFX=0
UNET DSS MLevel=0
UNET DZMax Abort=0
UNET Convert EG Bridges=0
UNET Use Existing IB Tables=0
UNET Froude Limit=0
UNET Froude Power=0
Write IC File=0
Echo Input=False
Echo Output=False
Write Detailed=0

--- BOONECK.f01 (steady flow) ---

Flow Title=2010 USGS WV Regression Equation
Program Version=4.00
Number of Profiles=1
Profile Names=P100yr
River Rch & RM=BOONECK,Main      ,6229.7
513.5664
River Rch & RM=BOONECK,Main      ,5974.3
515.2008
River Rch & RM=BOONECK,Main      ,5651.7
613.9381
River Rch & RM=BOONECK,Main      ,2253.2
660.8367
River Rch & RM=BOONECK,Main      ,2027.7
749.8241
River Rch & RM=BOONECK,Main      ,580.8
785.3829
River Rch & RM=BOONECK,Main      ,273.6
787.3204
Boundary for River Rch & Prof#=BOONECK,Main      ,1
Up Type=0
Dn Type=3
Dn Slope=0.026457

--- BOONECK.g01 (geometry) ---

Geom Title=LiDAR
Program Version=4.10

River Reach=BOONECK         ,Main
Reach XY= 30
     2034815.435      247275.947     2034884.873      247205.889
      2035000.15      246923.332     2035009.089      246750.616
     2035137.012      246637.989     2035171.244      246552.238
     2035283.484        246479.5      2035448.83      246468.142
     2035611.262      246401.028     2035809.873      246246.167
     2035993.206      246241.305     2036042.512      246191.306
     2036166.123      246153.805     2036375.845      245828.111
     2036741.867      245486.894     2036789.561      245303.458
     2036832.963      245255.715     2036960.568      245160.229
      2037146.07      245168.991     2037210.568      245138.528
     2037294.769      244873.771     2037444.943      244714.048
     2037457.963      244599.465     2037531.847      244489.517
     2037887.706      244330.351     2038254.531      244344.353
     2038404.373      244260.906     2038615.688        244216.3
     2039158.373      243991.551     2039363.683      243942.189

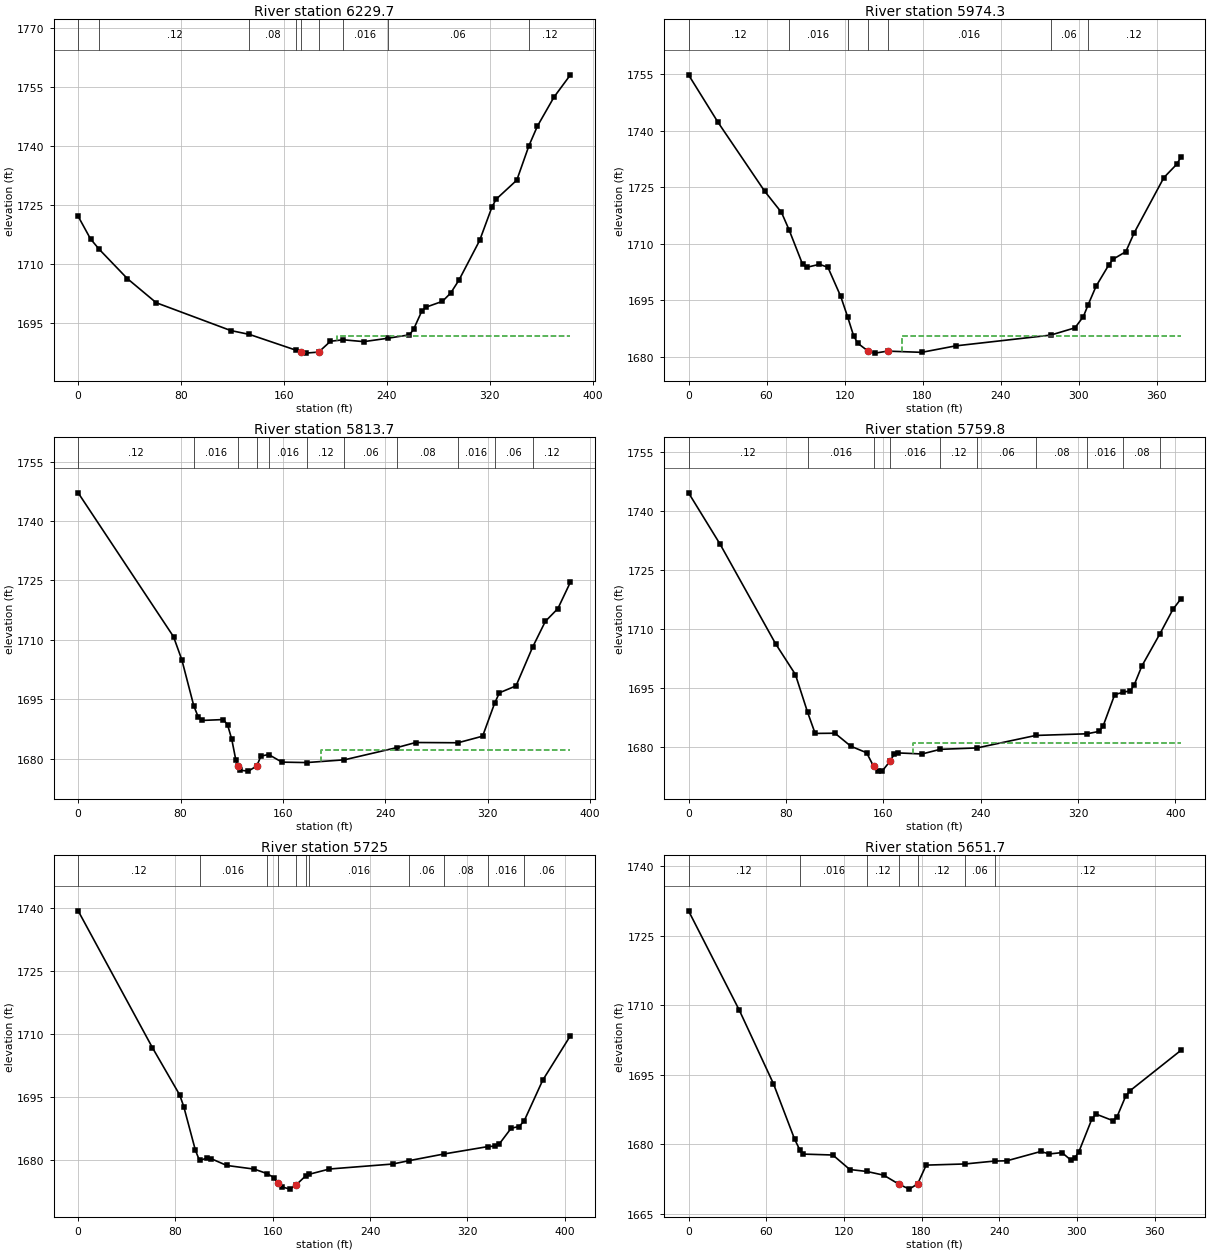
Type RM Length L Ch R = 1 ,6229.7  ,258.3,255.4,251.4
XS GIS Cut Line= 4
     2034996.583      247311.749     2034910.369      247310.001
     2034779.416      247215.061     2034656.952      247271.433
#Sta/Elev= 30
       0 1722.02     9.6 1716.28   16.441713.606    38.3 1706.16    60.7 1700.04
   118.6 1692.97  133.211691.976  169.691687.934   173.6 1687.43   176.8 1687.22
  187.061687.487   196.2 1690.24  206.171690.612   222.1 1690.14   240.7    1691
   257.6 1691.87   260.8 1693.26   267.2 1697.89   270.4  1698.9   283.3  1700.4
   289.7 1702.51   296.1 1705.78   312.2 1715.87   321.8 1724.39     325 1726.36
   341.1 1731.22  350.531739.975   357.1 1744.94     370 1752.33   382.8 1758.01
#Mann= 9 ,-1 , 0
       0    .016       0   16.44     .12       0  133.21     .08       0
  169.69     .06       0   173.6    .045       0  187.06     .08       0
  206.17    .016       0   240.7     .06       0  350.53     .12       0
#XS Ineff= 2 , 0
                          201.03         1691.49
Permanent Ineff=
       F       F
Bank Sta=173.6,187.06
XS Rating Curve= 0 ,0
Exp/Cntr=0.3,0.1

Type RM Length L Ch R = 1 ,5974.3  ,169.6,160.6,151
XS GIS Cut Line= 4
     2035081.787      247068.517     2034975.981      247051.228
     2034820.816      246973.103     2034723.371      246965.769
#Sta/Elev= 30
       0 1754.89    22.7 1742.26    58.5 1723.99    71.5 1718.32   77.231713.781
    87.7 1704.55      91 1703.75   100.7 1704.54   107.2 1703.74     117 1696.06
  122.351690.585   126.9 1685.61   130.2 1683.55  138.151681.464   143.3 1680.94
   153.1 1681.47   179.3 1681.15   205.5 1682.87  278.471685.723   297.2 1687.66
   303.7 1690.67   307.11693.603   313.5 1698.76   323.3 1704.42   326.5  1705.9
   336.3 1707.89   342.8 1712.94   365.6 1727.59   375.4  1731.1   378.6 1732.95
#Mann= 7 ,-1 , 0
       0     .12       0   77.23    .016       0  122.35     .12       0
  138.15    .045       0   153.1    .016       0  278.47     .06       0
   307.1     .12       0
#XS Ineff= 2 , 0
                          164.29         1685.41
Permanent Ineff=
       F       F
Bank Sta=138.15,153.1
XS Rating Curve= 0 ,0
Exp/Cntr=0.3,0.1

Type RM Length L Ch R = 1 ,5813.7  ,60.1,53.9,47.6
XS GIS Cut Line= 3
     2035125.195      246942.794      2035035.66      246890.638
     2034755.097      246875.051
#Sta/Elev= 30
       0  1747.1    74.5 1710.81      81 1704.98   90.311693.396    93.9 1690.46
    97.1 1689.68   113.4  1689.9   116.7  1688.6     120 1684.93   123.2 1679.68
  125.111678.195   126.5 1677.11     133 1676.89   139.61678.205   142.8 1680.69
  148.821681.079   159.2 1679.16  178.431679.049  208.011679.743  249.051682.831
   263.7 1684.11  296.761684.047     316 1685.71  325.391694.022   329.1 1696.65
   342.1  1698.4     3551708.122     365 1714.67   374.8  1717.9   384.6 1724.58
#Mann= 11 ,-1 , 0
       0     .12       0   90.31    .016       0  125.11    .045       0
   139.6     .12       0  148.82    .016       0  178.43     .12       0
  208.01     .06       0  249.05     .08       0  296.76    .016       0
  325.39     .06       0     355     .12       0
#XS Ineff= 2 , 0
                          189.89         1682.16
Permanent Ineff=
       F       F
Bank Sta=125.11,139.6
XS Rating Curve= 0 ,0
Exp/Cntr=0.3,0.1

Type RM Length L Ch R = 1 ,5759.8  ,34.9,34.8,35
XS GIS Cut Line= 4
     2035139.814      246901.613     2035040.607      246828.008
     2034875.677        246864.9     2034765.141      246847.594
#Sta/Elev= 30
       0 1744.68      26 1731.58    71.5 1706.31    87.8 1698.48   97.821688.867
     104  1683.5   120.3 1683.55   133.3 1680.25   146.3 1678.58  152.11 1675.09
     156 1673.91   159.3 1674.01   165.8 1676.53     169 1678.26   172.3 1678.54
   191.8 1678.27  206.741679.452  237.011679.809  285.281682.984  327.381683.405
   337.3 1684.02   340.5 1685.32   350.1 1693.37  357.281693.988   362.9 1694.33
   366.1 1695.82   372.4 1700.64  387.181708.794     398 1715.08   404.4 1717.68
#Mann= 10 ,-1 , 0
       0     .12       0   97.82    .016       0  152.11    .045       0
   165.8    .016       0  206.74     .12       0  237.01     .06       0
  285.28     .08       0  327.38    .016       0  357.28     .08       0
  387.18     .06       0
#XS Ineff= 2 , 0
                          184.21         1680.95
Permanent Ineff=
       F       F
Bank Sta=152.11,165.8
XS Rating Curve= 0 ,0
Exp/Cntr=0.3,0.1

Type RM Length L Ch R = 1 ,5725    ,55.4,73.3,90.7
XS GIS Cut Line= 4
     2035149.049      246870.344     2035043.255      246791.851
     2034878.324      246828.744     2034775.754      246812.685
#Sta/Elev= 30
       0  1739.4      61 1706.76    83.5 1695.44    86.8 1692.66    96.4 1682.22
   99.741679.828     106 1680.41   109.2 1680.26   122.1 1678.63   144.7 1677.76
  155.521676.658     161 1675.68   164.2 1674.44   167.5 1673.52     174 1672.98
  179.021673.953  186.951676.129  189.821676.519   206.5 1677.78   258.5 1678.97
  272.111679.782  301.031681.388  336.681683.127   342.9 1683.26   346.2 1683.79
   355.9 1687.52   362.4 1687.92  366.581689.262   381.8 1698.96   404.6  1709.6
#Mann= 11 ,-1 , 0
       0     .12       0   99.74    .016       0  155.52     .12       0
   164.2    .045       0  179.02     .12       0  186.95     .06       0
  189.82    .016       0  272.11     .06       0  301.03     .08       0
  336.68    .016       0  366.58     .06       0
Bank Sta=164.2,179.02
XS Rating Curve= 0 ,0
Exp/Cntr=0.3,0.1

Type RM Length L Ch R = 1 ,5651.7  ,276.4,285.4,291.7
XS GIS Cut Line= 2
     2035166.723      246822.407     2034843.709      246621.677
#Sta/Elev= 30
       0 1730.35    39.3 1708.87    65.6 1693.05      82 1681.05    86.21678.651
    88.5 1677.87   111.5 1677.67   124.6 1674.54  137.791674.119   150.8 1673.32
  162.571671.368   170.5 1670.31     177 1671.44   183.6 1675.49  213.721675.741
  236.461676.367   245.9 1676.42   272.1 1678.43   278.7  1677.9   288.5 1678.19
   295.1 1676.64   298.3 1676.98   301.6  1678.4   311.5 1685.36   314.7 1686.51
   327.8 1685.09   331.1 1685.96   337.7 1690.35     341 1691.52   380.3 1700.23
#Mann= 7 ,-1 , 0
       0     .12       0    86.2    .016       0  137.79     .12       0
  162.57    .045       0     177     .12       0  213.72     .06       0
  236.46     .12       0
Bank Sta=162.57,177
XS Rating Curve= 0 ,0
Exp/Cntr=0.3,0.1

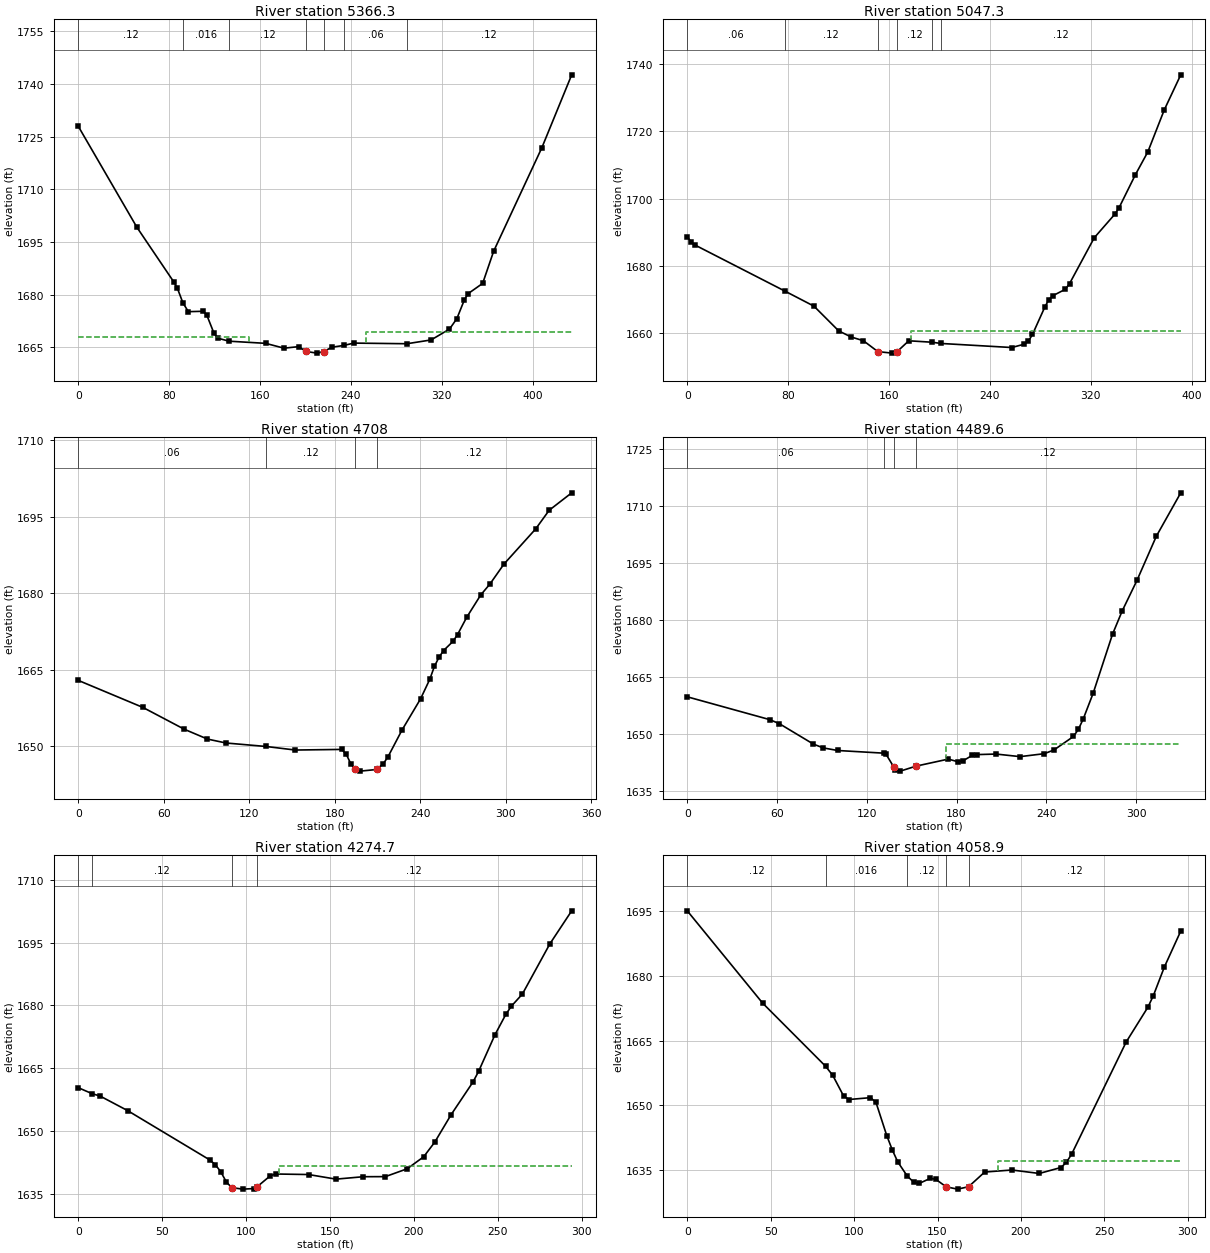
Type RM Length L Ch R = 1 ,5366.3  ,311.5,319,324.8
XS GIS Cut Line= 4
     2035312.655      246705.299     2035267.864       246608.52
     2035105.104      246411.037     2035075.596      246345.465
#Sta/Elev= 30
       0    1728    51.7 1699.16      84 1683.67    87.2 1681.89   92.21 1677.61
      97 1675.12   109.9 1675.23   113.1 1674.23   119.6 1668.92   122.8 1667.58
  132.691666.706     165 1666.09   181.2 1664.71   194.1 1665.15   200.6 1663.77
   210.3  1663.3  216.021663.717   223.3 1664.98  233.861665.493   242.7 1666.16
   289.41665.977   310.7 1667.06   326.9 1670.15   333.4 1673.14   339.9  1678.4
   343.1 1680.21   356.1 1683.18   365.8 1692.36   408.3 1721.91   434.5 1742.64
#Mann= 7 ,-1 , 0
       0     .12       0   92.21    .016       0  132.69     .12       0
   200.6    .045       0  216.02     .12       0  233.86     .06       0
   289.4     .12       0
#XS Ineff= 2 , 0
          150.67 1667.94  253.35         1669.29
Permanent Ineff=
       F       F
Bank Sta=200.6,216.02
XS Rating Curve= 0 ,0
Exp/Cntr=0.3,0.1

Type RM Length L Ch R = 1 ,5047.3  ,343.7,339.3,334.1
XS GIS Cut Line= 3
     2035521.023      246593.305     2035530.451      246519.544
      2035410.51      246226.052
#Sta/Elev= 30
       0  1688.6     3.2 1686.92     6.5 1686.06   77.381672.408   100.5  1667.9
   120.1 1660.54   129.9 1658.72   139.7  1657.6   151.2 1654.34   162.6  1653.9
   166.2 1654.27   175.7 1657.58  194.341657.146  201.281656.782   257.4 1655.57
   267.2 1656.56   270.5 1657.44   273.8 1659.46   283.6 1667.64   286.8 1669.86
   290.1 1671.05   299.9 1672.94   303.2 1674.62   322.8  1688.3   339.1 1695.31
   342.4  1697.2   355.5 1707.15   365.3 1713.91   378.3  1726.4   391.4 1736.88
#Mann= 6 ,-1 , 0
       0     .06       0   77.38     .12       0   151.2    .045       0
   166.2     .12       0  194.34     .06       0  201.28     .12       0
#XS Ineff= 2 , 0
                           177.5         1660.61
Permanent Ineff=
       F       F
Bank Sta=151.2,166.2
XS Rating Curve= 0 ,0
Exp/Cntr=0.3,0.1

Type RM Length L Ch R = 1 ,4708    ,210.5,218.4,226.1
XS GIS Cut Line= 4
     2035843.406       246456.58     2035810.399      246311.211
     2035722.508      246182.088     2035716.709      246141.492
#Sta/Elev= 30
       0 1662.89    45.4 1657.58    74.5 1653.29    90.7 1651.37   103.7  1650.6
   131.81649.917   152.3 1649.22   184.9 1649.34   188.1 1648.39   191.4 1646.45
   194.4 1645.48   197.9 1645.08   209.4  1645.4   214.2 1646.57   217.4  1647.9
   227.2 1653.13   240.2 1659.24   246.7 1663.09     250 1665.66   253.2 1667.43
   256.4 1668.75     263 1670.54   266.2 1671.88   272.7  1675.3   282.5 1679.66
     289 1681.82   298.8 1685.72     321  1692.6   330.5 1696.27   346.3 1699.69
#Mann= 4 ,-1 , 0
       0     .06       0   131.8     .12       0   194.4    .045       0
   209.4     .12       0
Bank Sta=194.4,209.4
XS Rating Curve= 0 ,0
Exp/Cntr=0.3,0.1

Type RM Length L Ch R = 1 ,4489.6  ,225.2,214.8,202.7
XS GIS Cut Line= 4
     2036002.779       246386.47     2035995.946      246263.468
     2035967.734      246158.216     2035916.461      246074.989
#Sta/Elev= 30
       0 1659.77    55.1 1653.76    61.6 1652.68    84.3 1647.31    90.8 1646.31
   100.5 1645.62  131.241644.919   132.8 1644.69   137.9 1641.37   139.2 1640.54
   142.4 1640.18   152.9 1641.49   174.5 1643.35   180.9 1642.66   184.1 1642.84
   190.5 1644.33   193.7 1644.54   206.5 1644.68   222.5    1644   238.7 1644.78
   245.2 1645.77   258.2 1649.32   261.5 1651.22   264.7 1653.92   271.3 1660.66
   284.3 1676.28   290.8 1682.44   300.6 1690.43   313.6 1702.11   329.9 1713.54
#Mann= 4 ,-1 , 0
       0     .06       0  131.24     .12       0   137.9    .045       0
   152.9     .12       0
#XS Ineff= 2 , 0
                          173.01         1647.43
Permanent Ineff=
       F       F
Bank Sta=137.9,152.9
XS Rating Curve= 0 ,0
Exp/Cntr=0.3,0.1

Type RM Length L Ch R = 1 ,4274.7  ,219.7,215.9,210
XS GIS Cut Line= 2
      2036239.56      246219.566      2036039.14      246004.422
#Sta/Elev= 30
       0 1660.32    8.121658.909    13.1  1658.3    29.4 1654.84    78.4 1643.03
    81.7 1641.89    84.9 1640.22    88.2  1637.8    91.4 1636.41      98 1636.05
   104.6 1636.18   106.4 1636.55   114.4 1639.23   117.6 1639.67   137.2 1639.54
   153.6 1638.44   169.9 1639.02     183 1639.04     196 1640.92   205.8 1643.78
   212.4 1647.28   222.2 1653.88   235.2 1661.68   238.5 1664.19   248.3 1672.98
   254.8 1677.88   258.1 1679.83   264.6  1682.7     281 1694.72     294 1702.62
#Mann= 4 ,-1 , 0
       0    .016       0    8.12     .12       0    91.4    .045       0
   106.4     .12       0
#XS Ineff= 2 , 0
                          119.81         1641.49
Permanent Ineff=
       F       F
Bank Sta=91.4,106.4
XS Rating Curve= 0 ,0
Exp/Cntr=0.3,0.1

Type RM Length L Ch R = 1 ,4058.9  ,160.8,159.2,157.4
XS GIS Cut Line= 3
       2036432.9      246039.943     2036329.062      246004.136
     2036177.456      245896.514
#Sta/Elev= 30
       0 1695.09    45.2  1673.7   82.891659.094    87.2 1656.98    93.7 1652.21
    96.9 1651.38   109.8 1651.81   113.1 1650.74   119.6    1643   122.9  1639.7
   126.2 1636.91  131.861633.658   135.9 1632.16   139.2 1631.97   145.7 1633.12
     149 1632.89  155.191631.151     162 1630.62   168.6 1631.17   178.3 1634.58
   194.6 1635.05     211 1634.25     224 1635.63   227.3 1636.83   230.5  1638.8
   263.1 1664.71   276.2 1672.82   279.4 1675.46     286 1682.09   295.8  1690.4
#Mann= 5 ,-1 , 0
       0     .12       0   82.89    .016       0  131.86     .12       0
  155.19    .045       0   168.6     .12       0
#XS Ineff= 2 , 0
                          186.38         1637.09
Permanent Ineff=
       F       F
Bank Sta=155.19,168.6
XS Rating Curve= 0 ,0
Exp/Cntr=0.3,0.1

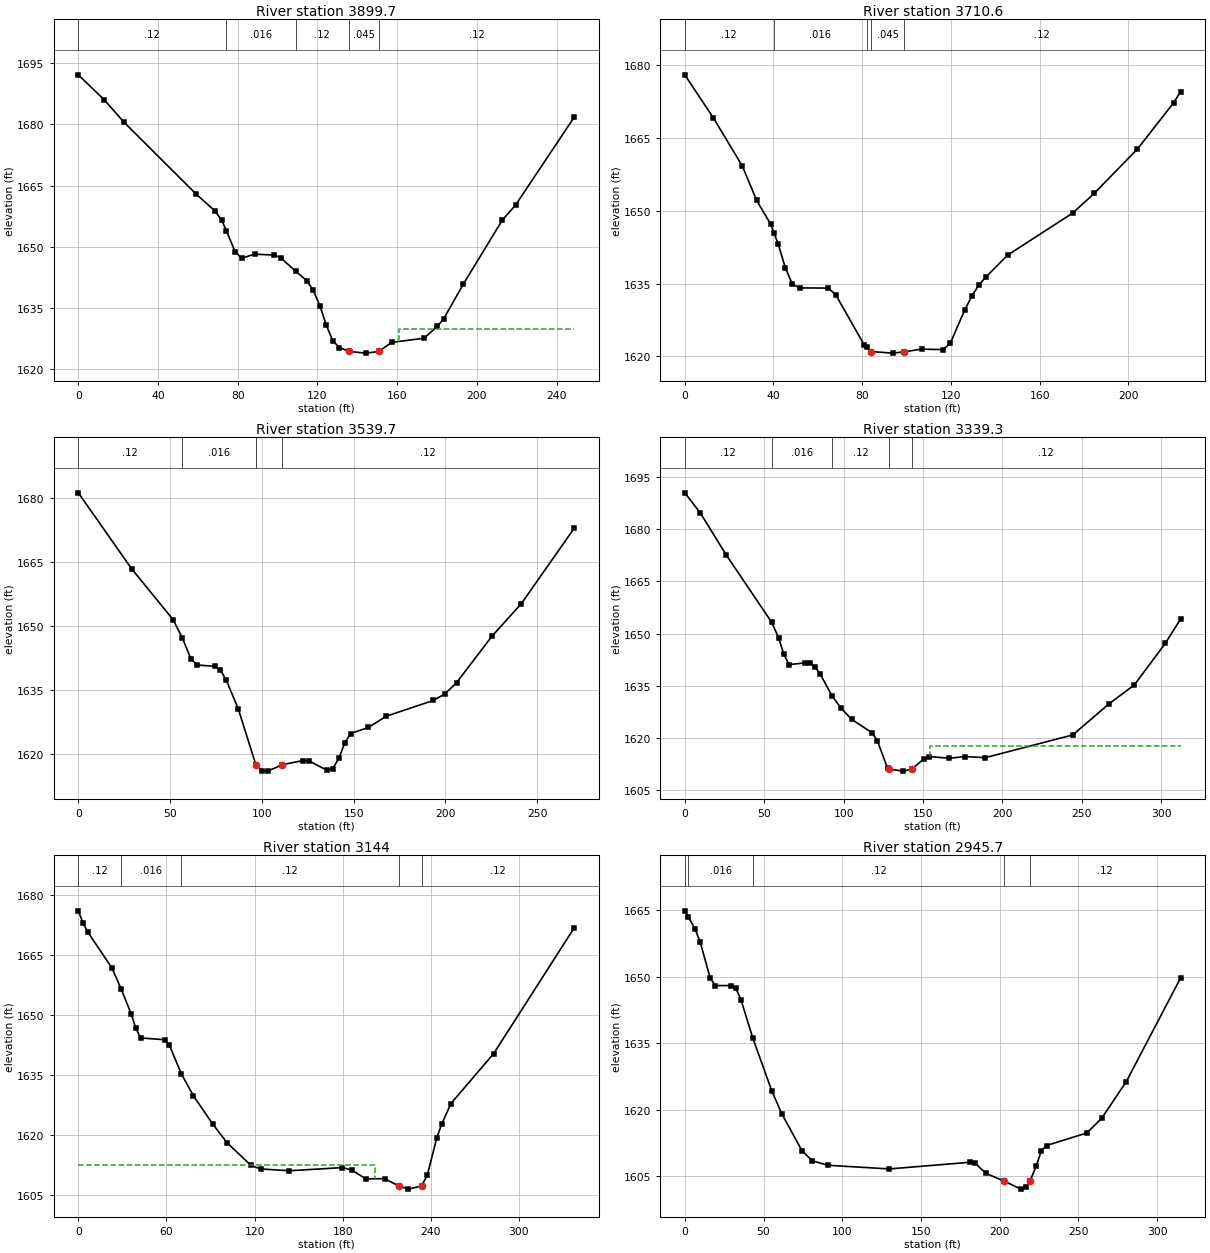
Type RM Length L Ch R = 1 ,3899.7  ,180.7,189,197
XS GIS Cut Line= 2
     2036490.738      245914.076     2036276.911      245786.798
#Sta/Elev= 30
       0 1692.15    13.1 1685.98    22.9 1680.55    58.9 1663.05    68.8  1658.7
      72 1656.49   74.241654.026    78.6 1648.88    81.9 1647.24    88.4 1648.23
    98.2 1648.02   101.5 1647.39  109.03 1644.04   114.6 1641.78   117.9 1639.34
   121.2 1635.62   124.4 1630.87   127.7 1627.01     131 1625.37   135.8 1624.42
   144.1    1624   150.8  1624.4   157.2 1626.63   173.5 1627.65   180.1 1630.54
   183.4 1632.46   193.2 1640.91   212.8 1656.61   219.4 1660.25   248.8 1681.76
#Mann= 5 ,-1 , 0
       0     .12       0   74.24    .016       0  109.03     .12       0
   135.8    .045       0   150.8     .12       0
#XS Ineff= 2 , 0
                          160.73            1630
Permanent Ineff=
       F       F
Bank Sta=135.8,150.8
XS Rating Curve= 0 ,0
Exp/Cntr=0.3,0.1

Type RM Length L Ch R = 1 ,3710.6  ,174.4,171,167.7
XS GIS Cut Line= 3
     2036567.778      245791.463     2036483.142      245685.126
     2036407.244      245641.139
#Sta/Elev= 30
       0 1678.02    12.9 1669.14    25.9 1659.27    32.4 1652.15    38.8 1647.19
   40.191645.505    42.1 1643.19    45.3 1638.31    48.5 1634.91    51.8 1634.12
    64.7 1634.08      68 1632.75    80.9 1622.39   81.991621.917    84.1    1621
    93.8 1620.68   98.831620.948   106.8  1621.5   116.5  1621.4   119.7 1622.69
   126.2 1629.53   129.4 1632.38   132.7  1634.8   135.9 1636.41   145.6 1640.88
   174.9 1649.53   184.6 1653.58   204.1 1662.72   220.4 1672.23   223.6 1674.58
#Mann= 5 ,-1 , 0
       0     .12       0   40.19    .016       0   81.99     .12       0
    84.1    .045       0   98.83     .12       0
Bank Sta=84.1,98.83
XS Rating Curve= 0 ,0
Exp/Cntr=0.3,0.1

Type RM Length L Ch R = 1 ,3539.7  ,207,200.4,191.6
XS GIS Cut Line= 3
     2036714.441      245677.989     2036589.479      245561.428
     2036497.135       245525.15
#Sta/Elev= 30
       0 1681.29      29 1663.47    51.6 1651.51   56.671647.202    61.3 1642.32
    64.5 1640.85    74.2 1640.55    77.4 1639.64    80.6 1637.28    87.1 1630.57
   96.661617.473    96.7 1617.42     100    1616   103.2 1615.92  111.151617.439
   122.5 1618.41   125.8 1618.29   135.4 1616.12   138.6 1616.52   141.9 1618.91
   145.1 1622.48   148.3 1624.75     158 1626.17   167.7 1628.81   193.3 1632.51
   199.7 1634.06   206.1 1636.73   225.3  1647.6   241.3 1655.24   270.1 1672.96
#Mann= 5 ,-1 , 0
       0     .12       0   56.67    .016       0   96.66     .12       0
    96.7    .045       0  111.15     .12       0
Bank Sta=96.7,111.15
XS Rating Curve= 0 ,0
Exp/Cntr=0.3,0.1

Type RM Length L Ch R = 1 ,3339.3  ,189.1,195.3,202.3
XS GIS Cut Line= 3
     2036849.481      245550.057     2036780.451      245458.346
     2036596.784      245385.872
#Sta/Elev= 30
       0 1690.48     9.8 1684.68    26.2 1672.54   54.741653.233      59 1648.86
    62.3 1644.17    65.6 1641.08    75.4 1641.57    78.7 1641.44      82  1640.5
    85.3 1638.31    92.71632.108    98.4 1628.57     105 1625.38     118 1621.45
   121.3 1619.17   127.7 1611.23  128.531611.066   137.4 1610.46  143.061611.071
   150.4 1613.93   153.6 1614.66   166.6 1614.16   176.3 1614.65   189.2 1614.34
   244.3 1620.87   266.9 1629.73   283.1 1635.27   302.5 1647.16   312.2 1654.21
#Mann= 5 ,-1 , 0
       0     .12       0   54.74    .016       0    92.7     .12       0
  128.53    .045       0  143.06     .12       0
#XS Ineff= 2 , 0
                          154.23         1617.57
Permanent Ineff=
       F       F
Bank Sta=128.53,143.06
XS Rating Curve= 0 ,0
Exp/Cntr=0.3,0.1

Type RM Length L Ch R = 1 ,3144    ,181.8,198.4,214.9
XS GIS Cut Line= 3
     2036943.212      245454.006     2036856.406      245304.267
      2036730.77       245198.03
#Sta/Elev= 30
       0 1676.11     3.3 1672.98     6.5 1670.76    22.9  1661.8    29.31656.431
    35.9 1650.39    39.2 1646.69    42.4 1644.31    58.8 1643.87      62 1642.48
   70.191635.293    78.4 1629.81    91.4 1622.82   101.2 1618.12   117.6 1612.41
   124.1 1611.54   143.7 1611.09   179.5 1611.87     186 1611.33   195.7 1609.06
   208.6  1609.1   218.2 1607.28   224.7 1606.49  233.691607.262   237.6 1609.99
   244.1 1619.35   247.3 1622.66   253.7  1627.9   282.8 1640.41   337.6 1671.83
#Mann= 5 ,-1 , 0
       0     .12       0    29.3    .016       0   70.19     .12       0
   218.2    .045       0  233.69     .12       0
#XS Ineff= 2 , 0
          202.27 1612.43
Permanent Ineff=
       F       F
Bank Sta=218.2,233.69
XS Rating Curve= 0 ,0
Exp/Cntr=0.3,0.1

Type RM Length L Ch R = 1 ,2945.7  ,214.6,206.2,196.4
XS GIS Cut Line= 4
     2037061.484      245345.499     2036986.614      245223.971
     2036971.423       245118.72     2036928.346      245068.774
#Sta/Elev= 30
       0 1664.87    2.271663.444     6.5 1660.79     9.7 1657.91    16.2 1649.62
    19.5 1647.99    29.2 1647.99    32.4 1647.39    35.7 1644.74   43.121636.237
    55.2 1624.27    61.6 1619.05    74.6  1610.6    81.1 1608.43    90.8 1607.42
   129.8 1606.59   181.4  1608.1   184.6 1607.86   191.1 1605.62     203 1603.82
   213.6 1602.03   216.9 1602.47  219.191603.753   223.3 1607.27   226.5 1610.69
   229.8 1611.88   255.4 1614.71   264.8    1618   280.5 1626.32     315 1649.73
#Mann= 5 ,-1 , 0
       0     .12       0    2.27    .016       0   43.12     .12       0
     203    .045       0  219.19     .12       0
Bank Sta=203,219.19
XS Rating Curve= 0 ,0
Exp/Cntr=0.3,0.1

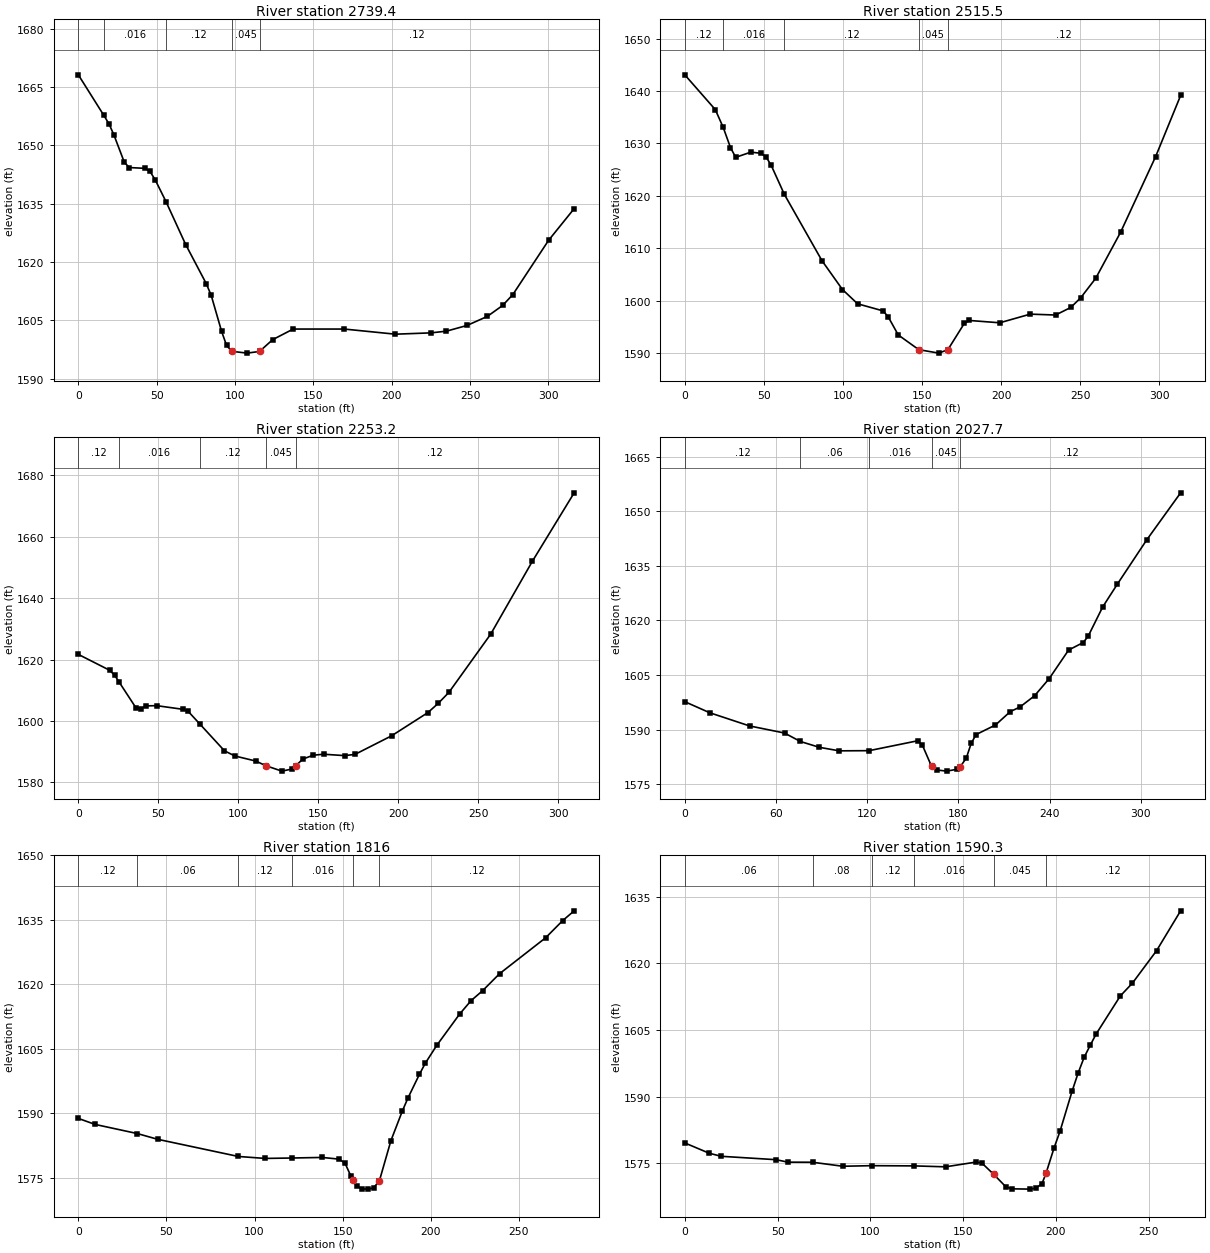
Type RM Length L Ch R = 1 ,2739.4  ,242.1,224,205
XS GIS Cut Line= 3
     2037233.737      245249.558     2037136.354      245087.253
     2037032.629      245013.702
#Sta/Elev= 30
       0 1668.16   16.321657.707    19.6 1655.53    22.8 1652.61    29.4 1645.62
    32.6 1644.32    42.4 1644.12    45.7 1643.33      49 1641.21   55.98 1635.53
    68.5 1624.53    81.6  1614.5    84.8 1611.45    91.4 1602.23    94.6 1598.58
    97.9 1597.08   107.7 1596.61  115.621597.041     124 1600.07   137.1  1602.8
   169.7  1602.8   202.3 1601.48   225.1 1601.82   234.9 1602.26     248 1603.72
     261 1606.05   270.8 1608.88   277.3 1611.68   300.1 1625.62   316.4 1633.76
#Mann= 5 ,-1 , 0
       0     .12       0   16.32    .016       0   55.98     .12       0
    97.9    .045       0  115.62     .12       0
Bank Sta=97.9,115.62
XS Rating Curve= 0 ,0
Exp/Cntr=0.3,0.1

Type RM Length L Ch R = 1 ,2515.5  ,255,262.3,268.9
XS GIS Cut Line= 4
     2037414.132      245019.978     2037305.625       244971.15
     2037189.522      244946.194     2037134.437      244894.086
#Sta/Elev= 30
       0  1643.1    19.3 1636.46   24.311633.052    28.9 1629.21    32.2 1627.36
    41.8 1628.35    48.2 1628.13    51.4 1627.45    54.7  1625.8   62.971620.291
    86.8 1607.62    99.7 1602.14   109.3 1599.41   125.4 1598.06   128.6 1596.95
     135 1593.47     148 1590.66   160.7    1590  166.431590.676   176.8 1595.68
     180 1596.23   199.2 1595.79   218.5 1597.44   234.5 1597.27   244.1 1598.71
   250.4 1600.56   259.9 1604.28   275.6 1613.05   297.8  1627.5   313.6 1639.16
#Mann= 5 ,-1 , 0
       0     .12       0   24.31    .016       0   62.97     .12       0
     148    .045       0  166.43     .12       0
Bank Sta=148,166.43
XS Rating Curve= 0 ,0
Exp/Cntr=0.3,0.1

Type RM Length L Ch R = 1 ,2253.2  ,226.2,225.4,223.8
XS GIS Cut Line= 2
     2037523.955      244822.171     2037254.627      244668.416
#Sta/Elev= 30
       0 1621.69    19.6 1616.52    22.8 1614.84    25.31612.855    35.9  1604.4
    39.2 1604.06    42.4 1604.93      49    1605    65.3 1603.82    68.6  1603.2
   76.191598.913    91.4  1590.3    97.9 1588.62     111 1586.97   117.2 1585.47
   127.3 1583.69   133.8 1584.39   136.11585.498   140.4 1587.62   146.9 1588.87
   153.4 1589.19   166.5 1588.74     173 1589.13   195.9 1595.18   218.7 1602.77
   225.2 1605.81   231.8 1609.35   257.9 1628.28     284 1652.03   310.1 1674.28
#Mann= 5 ,-1 , 0
       0     .12       0    25.3    .016       0   76.19     .12       0
   117.2    .045       0   136.1     .12       0
Bank Sta=117.2,136.1
XS Rating Curve= 0 ,0
Exp/Cntr=0.3,0.1

Type RM Length L Ch R = 1 ,2027.7  ,198.2,211.7,225
XS GIS Cut Line= 4
     2037596.992      244674.068     2037545.425      244582.695
     2037433.663      244526.272     2037337.669      244529.794
#Sta/Elev= 30
       0 1597.65    16.4 1594.61    42.6 1590.98    65.6 1589.03   76.021586.709
    88.5  1585.1   101.6 1584.13  121.251584.178   153.1 1586.89   156.3  1585.7
  162.381579.825   165.9 1578.86   172.3 1578.55   178.8 1579.04   181.3 1579.82
   185.2 1582.14   188.4 1586.17   191.6  1588.6   204.4 1591.24   214.1 1594.91
   220.5 1596.19   230.1 1599.27   239.7 1603.98   252.5 1611.85   262.1 1613.92
   265.3  1615.6   274.9 1623.69   284.6    1630   303.8  1642.1   326.2  1655.1
#Mann= 5 ,-1 , 0
       0     .12       0   76.02     .06       0  121.25    .016       0
  162.38    .045       0   181.3     .12       0
Bank Sta=162.38,181.3
XS Rating Curve= 0 ,0
Exp/Cntr=0.3,0.1

Type RM Length L Ch R = 1 ,1816    ,221.9,225.7,229.2
XS GIS Cut Line= 3
     2037684.314      244592.461     2037672.378      244470.933
     2037594.633      244331.907
#Sta/Elev= 30
       0 1588.83     9.6 1587.43   33.541585.306      45 1583.98   90.771579.987
     106 1579.53  121.451579.628   138.4 1579.76   148.1 1579.36   151.4 1578.38
   154.6  1575.5  156.111574.413   157.9 1573.12   161.1 1572.45   164.4 1572.39
   167.6 1572.68   170.9 1574.38   177.4 1583.66   183.9 1590.57   187.1  1593.6
   193.6  1599.1   196.9 1601.66   203.4 1605.81   216.4  1613.1   222.9 1616.23
   229.4 1618.52   239.1  1622.5   265.2 1630.84   274.9 1634.84   281.4 1637.11
#Mann= 6 ,-1 , 0
       0     .12       0   33.54     .06       0   90.77     .12       0
  121.45    .016       0  156.11    .045       0   170.9     .12       0
Bank Sta=156.11,170.9
XS Rating Curve= 0 ,0
Exp/Cntr=0.3,0.1

Type RM Length L Ch R = 1 ,1590.3  ,245,252.3,259.5
XS GIS Cut Line= 3
     2037874.014       244518.11     2037878.541      244400.404
     2037827.417      244260.042
#Sta/Elev= 30
       0  1579.6    13.1 1577.29    19.6 1576.59    49.1 1575.83    55.6 1575.27
   68.851575.252    85.1 1574.35  100.73 1574.48   123.6 1574.43   140.5 1574.22
   156.8 1575.28     160 1575.11   166.5 1572.51     173 1569.73   176.2 1569.27
     186  1569.2   189.2  1569.4   192.5 1570.45  194.631572.726     199 1578.48
   202.2 1582.22   208.7 1591.23     212 1595.38   215.2 1598.86   218.5  1601.6
   221.7 1604.14   234.7 1612.69   241.2 1615.56   254.2 1622.86   267.2 1631.85
#Mann= 6 ,-1 , 0
       0     .06       0   68.85     .08       0  100.73     .12       0
   123.6    .016       0   166.5    .045       0  194.63     .12       0
Bank Sta=166.5,194.63
XS Rating Curve= 0 ,0
Exp/Cntr=0.3,0.1

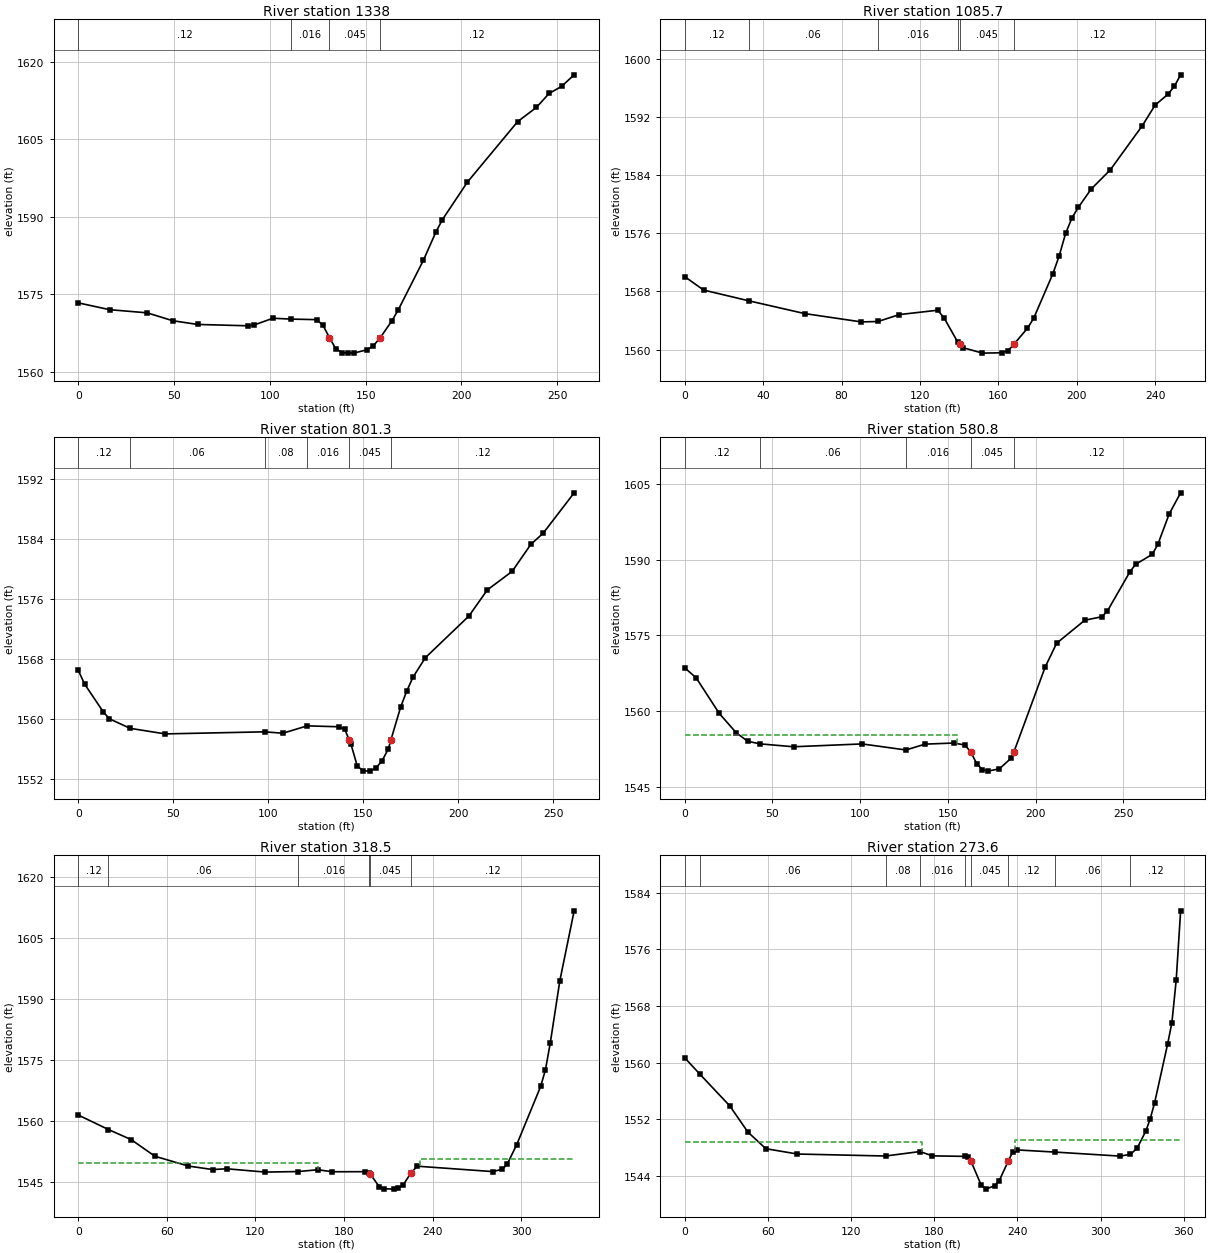
Type RM Length L Ch R = 1 ,1338    ,264.1,252.3,239.7
XS GIS Cut Line= 2
     2038108.895      244495.988      2038100.92       244237.24
#Sta/Elev= 30
       0 1573.31    16.4 1571.99      36 1571.38    49.2 1569.86    62.3 1569.13
    88.5 1568.87    91.8 1569.03   101.6 1570.33  111.121570.168   124.5 1570.06
   127.8 1568.95   131.1 1566.57   134.4 1564.45   137.6 1563.69   140.9 1563.57
   144.2 1563.61   150.7 1564.22     154 1564.97  157.731566.597   163.8 1569.87
   167.1 1571.99   180.2 1581.59   186.8 1587.13   190.1 1589.45   203.2 1596.75
   229.4 1608.46   239.2 1611.22   245.8 1613.91   252.3 1615.28   258.9 1617.53
#Mann= 4 ,-1 , 0
       0     .12       0  111.12    .016       0   131.1    .045       0
  157.73     .12       0
Bank Sta=131.1,157.73
XS Rating Curve= 0 ,0
Exp/Cntr=0.3,0.1

Type RM Length L Ch R = 1 ,1085.7  ,278.9,284.4,289.7
XS GIS Cut Line= 3
     2038400.913      244440.611     2038376.588      244347.235
     2038292.089      244215.488
#Sta/Elev= 30
       0 1570.02     9.6 1568.18   32.551566.709    61.1 1564.95    90.1  1563.8
   98.551563.859   109.5 1564.81   129.1 1565.41   132.4  1564.3  139.221561.051
  140.34 1560.74   142.1 1560.25   151.9 1559.51   161.7 1559.56     165 1559.84
   168.2 1560.82   174.8 1562.91     178 1564.29   187.8 1570.41     191 1572.85
   194.3 1575.96   197.6 1578.12   200.8 1579.55   207.4 1582.08   217.1  1584.7
   233.4 1590.76     240 1593.61   246.5 1595.09   249.8 1596.19     253 1597.77
#Mann= 6 ,-1 , 0
       0     .12       0   32.55     .06       0   98.55    .016       0
  139.22     .12       0  140.34    .045       0   168.2     .12       0
Bank Sta=140.34,168.2
XS Rating Curve= 0 ,0
Exp/Cntr=0.3,0.1

Type RM Length L Ch R = 1 ,801.3   ,221.5,220.5,219.4
XS GIS Cut Line= 2
     2038662.853      244361.329     2038578.192      244114.552
#Sta/Elev= 30
       0 1566.44     3.3 1564.63      13 1560.97    16.3 1560.01   27.221558.732
    45.7 1557.99   97.961558.266   107.6 1558.08  120.451559.063     137 1558.94
   140.2 1558.61  142.491557.201   143.5 1556.58   146.8 1553.68     150 1553.07
  153.28 1553.03   156.5 1553.41   159.8  1554.4   163.1 1555.97   164.51557.208
   169.6 1561.57   172.8 1563.69   176.1 1565.55   182.6 1568.14   205.5 1573.69
   215.2 1577.17   228.3 1579.65   238.1 1583.24   244.6 1584.73   260.9 1590.11
#Mann= 6 ,-1 , 0
       0     .12       0   27.22     .06       0   97.96     .08       0
  120.45    .016       0  142.49    .045       0   164.5     .12       0
Bank Sta=142.49,164.5
XS Rating Curve= 0 ,0
Exp/Cntr=0.3,0.1

Type RM Length L Ch R = 1 ,580.8   ,262,262.3,262.5
XS GIS Cut Line= 3
     2038883.418      244300.186     2038805.191      244103.095
     2038795.957      244033.074
#Sta/Elev= 30
       0 1568.53     6.5 1566.55    19.6 1559.53    29.4 1555.64    35.9 1553.99
   42.721553.479      62  1552.9   101.1 1553.46   126.1 1552.26     137 1553.42
   153.3 1553.64   159.8 1553.24   163.1 1551.81   166.4 1549.58   169.6 1548.39
   172.9 1548.07   179.4 1548.54     186 1550.62   187.61551.823   205.5 1568.72
     212 1573.42   228.1 1577.99   237.7 1578.66   240.9 1579.77   253.8 1587.58
     257 1589.05   266.6 1591.05   269.8  1593.1   276.2 1599.05   282.7 1603.23
#Mann= 5 ,-1 , 0
       0     .12       0   42.72     .06       0   126.1    .016       0
   163.1    .045       0   187.6     .12       0
#XS Ineff= 2 , 0
          155.11 1555.25
Permanent Ineff=
       F       F
Bank Sta=163.1,187.6
XS Rating Curve= 0 ,0
Exp/Cntr=0.3,0.1

Type RM Length L Ch R = 1 ,318.5   ,43,44.9,46.7
XS GIS Cut Line= 4
     2039079.586      244245.805     2039077.543      244080.308
     2039035.226      243969.631     2038995.089      243936.719
#Sta/Elev= 30
       0 1561.52   20.431557.957    35.7  1555.5    51.9 1551.39    74.6 1548.98
    90.9 1548.13   100.6 1548.31   126.6  1547.5  149.041547.631   162.3 1548.08
   171.9 1547.58   194.3  1547.6  197.231547.188   197.5 1547.15   203.9 1543.89
   207.1 1543.41   213.6 1543.31   216.8 1543.52     220 1544.32  225.331547.271
   229.6 1548.95   280.8 1547.62   287.2  1548.2   290.5 1549.41     297 1554.25
   313.2 1568.55   316.4 1572.58   319.7  1579.2   326.2 1594.55   335.9 1611.73
#Mann= 6 ,-1 , 0
       0     .12       0   20.43     .06       0  149.04    .016       0
  197.23     .12       0   197.5    .045       0  225.33     .12       0
#XS Ineff= 2 , 0
          162.54 1549.73  231.17         1550.68
Permanent Ineff=
       F       F
Bank Sta=197.5,225.33
XS Rating Curve= 0 ,0
Exp/Cntr=0.3,0.1

Type RM Length L Ch R = 1 ,273.6   ,58.1,58.1,58.1
XS GIS Cut Line= 4
     2039114.038      244236.255     2039118.776      244077.053
     2039076.458      243931.654     2039034.353      243910.601
#Sta/Elev= 30
       0 1560.68   10.961558.365    32.5  1553.9    45.5 1550.22    58.5 1547.87
    81.3 1547.12  144.86 1546.84  169.731547.472   178.6 1546.86  202.191546.792
   204.4 1546.75  206.461546.126     214 1542.69   217.3 1542.17   223.7 1542.66
   226.9 1543.36   233.4 1546.12   236.6 1547.41   239.8  1547.7  267.331547.393
   313.8 1546.83  321.45 1547.06   326.4 1547.93   332.7 1550.37   335.8 1552.05
     339 1554.32   348.4 1562.62   351.5 1565.65   354.6 1571.63   357.8 1581.42
#Mann= 9 ,-1 , 0
       0     .12       0   10.96     .06       0  144.86     .08       0
  169.73    .016       0  202.19     .12       0  206.46    .045       0
   233.4     .12       0  267.33     .06       0  321.45     .12       0
#XS Ineff= 2 , 0
           170.9 1548.78   238.6         1549.12
Permanent Ineff=
       F       F
Bank Sta=206.46,233.4
XS Rating Curve= 0 ,0
Exp/Cntr=0.3,0.1

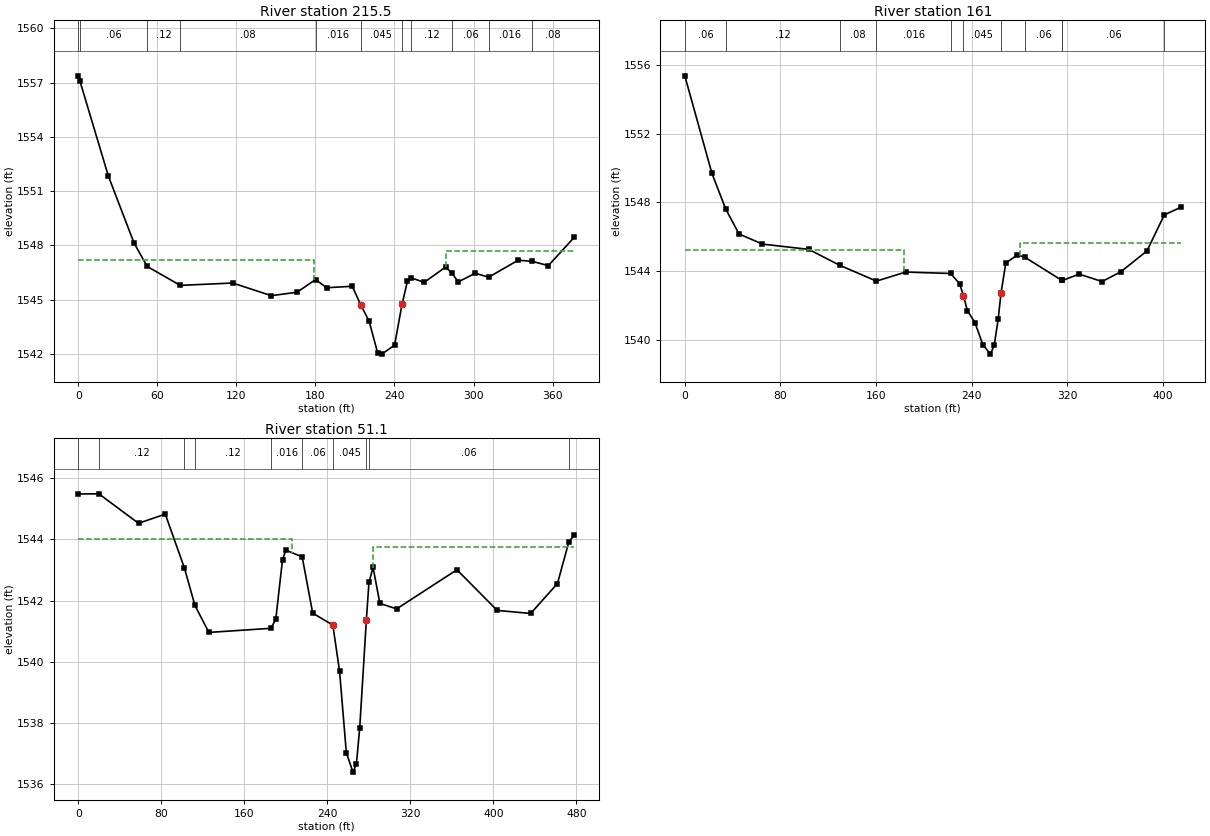
Type RM Length L Ch R = 1 ,215.5   ,55.7,54.5,53.6
XS GIS Cut Line= 4
     2039169.412      244220.337     2039174.158      244060.864
      2039131.84      243915.464     2039073.345      243886.217
#Sta/Elev= 30
       0 1557.37     1.11557.107    22.8 1551.83    42.3 1548.13   52.241546.837
   77.381545.789   117.2 1545.92   146.5 1545.22     166 1545.41  180.121546.111
   188.5 1545.66   207.9 1545.74   214.3 1544.73   220.8  1543.8   227.2 1542.06
   230.4 1541.99   240.1 1542.49  245.711544.737   249.8 1546.01  252.911546.195
   262.6 1545.96   278.8  1546.8  283.671546.467   288.4 1545.98   301.3 1546.46
  311.471546.241   333.9 1547.18   344.51547.119   356.8 1546.88   376.4 1548.44
#Mann= 11 ,-1 , 0
       0     .12       0     1.1     .06       0   52.24     .12       0
   77.38     .08       0  180.12    .016       0   214.3    .045       0
  245.71    .016       0  252.91     .12       0  283.67     .06       0
  311.47    .016       0   344.5     .08       0
#XS Ineff= 2 , 0
          179.15 1547.18  279.05         1547.69
Permanent Ineff=
       F       F
Bank Sta=214.3,245.71
XS Rating Curve= 0 ,0
Exp/Cntr=0.3,0.1

Type RM Length L Ch R = 1 ,161     ,107,109.8,112.7
XS GIS Cut Line= 4
      2039183.66      244216.955     2039229.453      244044.501
     2039174.114      243882.826     2039113.266      243858.106
#Sta/Elev= 30
       0 1555.36    22.7 1549.68   34.371547.581    45.4 1546.15    64.9 1545.56
   103.8 1545.25  129.851544.318  160.411543.403   184.9 1543.93  222.461543.848
     230 1543.25   233.2 1542.56   236.5 1541.69   242.9 1540.98   249.4 1539.71
   255.8 1539.15     259 1539.67   262.3 1541.19  264.731542.739   268.7 1544.46
   278.4 1544.93   284.9 1544.78  315.69 1543.44  316.12 1543.44     330 1543.81
   349.3 1543.38     365 1543.95   386.8 1545.16  401.331547.258     415  1547.7
#Mann= 11 ,-1 , 0
       0     .06       0   34.37     .12       0  129.85     .08       0
  160.41    .016       0  222.46     .12       0   233.2    .045       0
  264.73     .12       0   284.9     .06       0  315.69     .08       0
  316.12     .06       0  401.33    .016       0
#XS Ineff= 2 , 0
          183.69 1545.24  280.19          1545.6
Permanent Ineff=
       F       F
Bank Sta=233.2,264.73
XS Rating Curve= 0 ,0
Exp/Cntr=0.3,0.1

Type RM Length L Ch R = 1 ,51.1    ,51.7,51.1,50.6
XS GIS Cut Line= 4
     2039253.927      244197.476      2039333.62      244049.926
     2039301.068      243891.506      2039171.12      243819.621
#Sta/Elev= 30
       0 1545.49   19.781545.494      58 1544.53    83.8 1544.83  102.321543.059
   112.41541.842   125.8 1540.96   185.61541.095   190.3 1541.39   196.8 1543.34
     200 1543.65  215.761543.432   225.9 1541.59   245.3  1541.2   251.8 1539.69
   258.3 1537.03   264.7 1536.39     268 1536.65   271.2 1537.83  277.651541.382
  280.121542.597   284.1 1543.09   290.6 1541.91   306.8 1541.73   364.9 1543.01
   403.7 1541.68     436 1541.58   461.8 1542.56  472.831543.927   477.9 1544.14
#Mann= 10 ,-1 , 0
       0     .06       0   19.78     .12       0  102.32     .06       0
   112.4     .12       0   185.6    .016       0  215.76     .06       0
   245.3    .045       0  277.65     .12       0  280.12     .06       0
  472.83     .12       0
#XS Ineff= 2 , 0
          205.88 1544.02  284.31         1543.74
Permanent Ineff=
       F       F
Bank Sta=245.3,277.65
XS Rating Curve= 0 ,0
Exp/Cntr=0.3,0.1

Chan Stop Cuts=-1
Use User Specified Reach Order=0
Composite Channel Slope=5